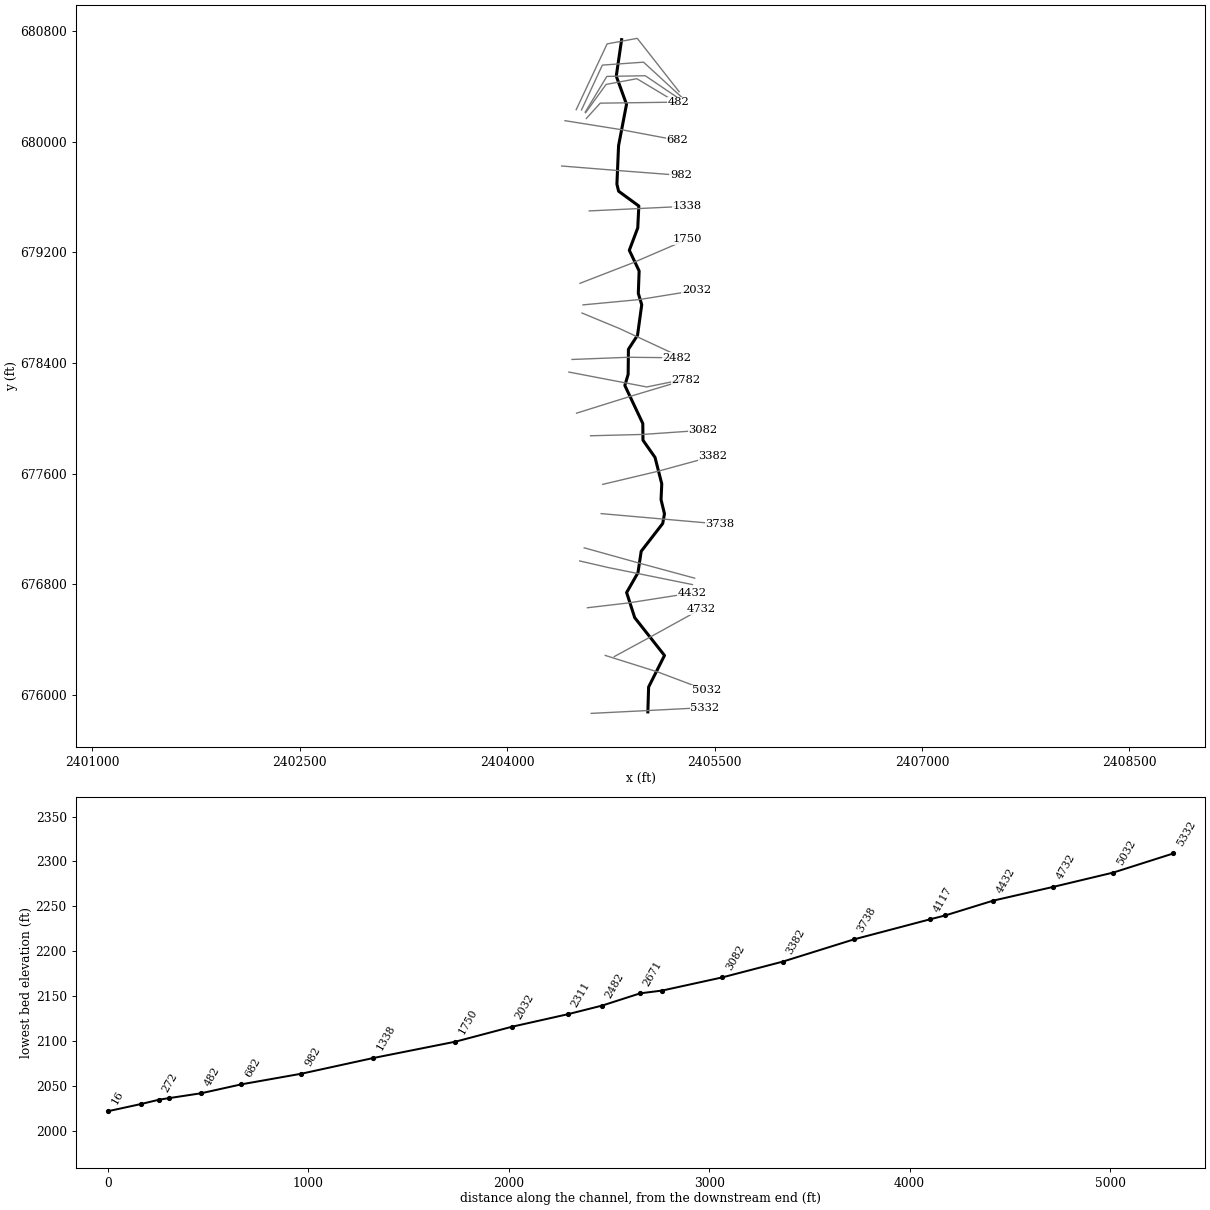
--- STRADERRN.prj (project) ---

Proj Title=STRADERRN
Current Plan=p01
Default Exp/Contr=0,0
English Units
Geom File=g01
Flow File=f01
Plan File=p01
BEGIN DESCRIPTION:
Stream Name: Strader Run
Flood Zone: Approximate
Pendleton County, West Virginia
HEC-RAS Version: 5.0.7
Hydrology Method:
Regression equation
END DESCRIPTION:
DSS Export Rating Curves= 0
DSS Export Rating Curve Sorted= 0
DSS Export Volume Flow Curves= 0
DXF OffsetX= 0
DXF OffsetY= 0
DXF ScaleX= 0
DXF ScaleY= 0

--- STRADERRN.p01 (plan) ---

Plan Title=Floodplain
Program Version=5.07
Short Identifier=Floodplain
Geom File=g01
Flow File=f01
Subcritical Flow
K Sum by GR= 0
Std Step Tol= 0.01
Critical Tol= 0.01
Num of Std Step Trials= 20
Max Error Tol= 0.3
Flow Tol Ratio= 0.001
Split Flow NTrial= 30
Split Flow Tol= 0.02
Split Flow Ratio= 0.02
Log Output Level= 0
Friction Slope Method= 1
Unsteady Friction Slope Method= 2
Unsteady Bridges Friction Slope Method= 1
Parabolic Critical Depth
Global Vel Dist= 0 , 0 , 0
Global Log Level= 0
CheckData=False
Encroach Param=-1 ,0,0, 0
Mapping Interval=1HOUR
Computation Time Step Use Courant=        0
Computation Time Step Use Time Series=    0
Computation Time Step Count To Double=0
Computation Time Step Max Doubling=0
Computation Time Step Max Halving=0
Computation Time Step Residence Courant=0
Run HTab= 0
Run UNet= 0
Run Sediment= 0
Run PostProcess= 0
Run WQNet= 0
Run RASMapper= 0
UNET Theta= 0
UNET Theta Warmup= 0
UNET ZTol= 0
UNET ZSATol= 0
UNET MxIter= 0
UNET Max Iter WO Improvement= 0
UNET MaxInSteps= 0
UNET DtIC= 0
UNET DtMin= 0
UNET MaxCRTS= 0
UNET WFStab= 0
UNET SFStab= 0
UNET WFX= 1
UNET SFX= 1
UNET 1D Methodology=Finite Difference
UNET DSS MLevel= 1
UNET Pardiso=0
UNET DZMax Abort= 0
UNET Use Existing IB Tables= 0
UNET Froude Reduction=False
UNET Froude Limit= 0
UNET Froude Power= 0
UNET D1 Cores= 0
UNET D2 Coriolis=0
UNET D2 Cores= 0
UNET D2 Theta= 1
UNET D2 Theta Warmup= 1
UNET D2 Z Tol= 0.01
UNET D2 Volume Tol= 0.01
UNET D2 Max Iterations= 20
UNET D2 Equation= 0
UNET D2 RampUpFraction=0.1
UNET D2 TimeSlices= 1
UNET D2 BCVolumeCheck=0
UNET D1D2 MaxIter= 0
UNET D1D2 ZTol=0.01
UNET D1D2 QTol=0.1
UNET D1D2 MinQTol=1
Write IC File= 0
Write IC File at Fixed DateTime=0
Write IC File at Sim End=0
Echo Input=False
Echo Parameters=False
Echo Output=False
Write Detailed= 0
HDF Write Warmup=0
HDF Write Time Slices=0
HDF Flush=0
HDF Face Node Velocities=0
HDF Compression= 1
HDF Chunk Size= 1
HDF Spatial Parts= 1
HDF Use Max Rows=0
HDF Fixed Rows= 1
Calibration Method= 0
Calibration Iterations= 20
Calibration Max Change=0.05
Calibration Tolerance=0.2
Calibration Maximum=1.5
Calibration Minimum=0.5
Calibration Optimization Method= 1
WQ AD Non Conservative
WQ ULTIMATE=-1
WQ Max Comp Step=1HOUR
WQ Output Interval=15MIN
WQ Output Selected Increments= 0
WQ Output face flow=0
WQ Output face velocity=0
WQ Output face area=0
WQ Output face dispersion=0
WQ Output cell volume=0
WQ Output cell surface area=0
WQ Output cell continuity=0
WQ Output cumulative cell continuity=0
WQ Output face conc=0
WQ Output face dconc_dx=0
WQ Output face courant=0
WQ Output face peclet=0
WQ Output face adv mass=0
WQ Output face disp mass=0
WQ Output cell mass=0
WQ Output cell source sink temp=0
WQ Output nsm pathways=0
WQ Output nsm derived pathways=0
WQ Output MaxMinRange=-1
WQ Daily Max Min Mean=-1
WQ Daily Range=0
WQ Daily Time=0
WQ Create Restart=0
WQ Fixed Restart=0
WQ System Summary=0
WQ Write To DSS=0
WQ Use Fixed Temperature=0
Sorting and Armoring Iterations= 10
XS Update Threshold= 0.02
Bed Roughness Predictor= 0
Hydraulics Update Threshold= 0.02
Energy Slope Method= 1
Volume Change Method= 1
Sediment Retention Method= 0
XS Weighting Method= 0
Number of US Weighted Cross Sections= 1
Number of DS Weighted Cross Sections= 1
Upstream XS Weight=0
Main XS Weight=1
Downstream XS Weight=0
Number of DS XS's Weighted with US Boundary= 1
Upstream Boundary Weight= 1
Weight of XSs Associated with US Boundary= 0
Number of US XS's Weighted with DS Boundary= 1
Downstream Boundary Weight= 0.5
Weight of XSs Associated with DS Boundary= 0.5
Percentile Method= 0
Sediment Output Level= 3
Mass or Volume Output= 0
Output Increment Type= 1
Profile and TS Output Increment= 1
XS Output Flag= 0
XS Output Increment= 10
Write Gradation File= 0
Read Gradation Hotstart= 0
Write HDF5 File= 1
Write Binary Output= 1
Write DSS Sediment File= 0
SV Curve= 0
Specific Gage Flag= 0

--- STRADERRN.f01 (steady flow) ---

Flow Title=Flows
Program Version=5.07
Number of Profiles= 6
Profile Names=P100yr,P10yr,P25yr,P50yr,P500yr,P101yr
River Rch & RM=STRADERRN,Main            ,5332
     553     259     365     456     810     673
River Rch & RM=STRADERRN,Main            ,4732
     720     336     475     594    1058     876
River Rch & RM=STRADERRN,Main            ,4117
     808     376     533     666    1188     983
Boundary for River Rch & Prof#=STRADERRN,Main            , 1
Up Type= 0
Dn Type= 3
Dn Slope=0.04104
Boundary for River Rch & Prof#=STRADERRN,Main            , 2
Up Type= 0
Dn Type= 3
Dn Slope=0.04104
Boundary for River Rch & Prof#=STRADERRN,Main            , 3
Up Type= 0
Dn Type= 3
Dn Slope=0.04104
Boundary for River Rch & Prof#=STRADERRN,Main            , 4
Up Type= 0
Dn Type= 3
Dn Slope=0.04104
Boundary for River Rch & Prof#=STRADERRN,Main            , 5
Up Type= 0
Dn Type= 3
Dn Slope=0.04104
Boundary for River Rch & Prof#=STRADERRN,Main            , 6
Up Type= 0
Dn Type= 3
Dn Slope=0.04104
DSS Import GetInterval= 0
DSS Import GetPeak= 0
DSS Import FillOption= 0

--- STRADERRN.g01 (geometry) ---

Geom Title=Geometry
Program Version=5.07

River Reach=STRADERRN       ,Main
Reach XY= 30
     2405018.124      675878.047     2405023.759      676058.308
     2405138.512      676286.156     2404923.298      676559.392
     2404864.698      676741.126     2404946.598      676883.877
     2404970.126      677039.293     2405125.533      677240.054
     2405138.418      677309.866     2405113.569       677412.38
     2405118.727      677527.027     2405069.981      677718.077
     2404982.943        677842.2     2404981.645      677963.178
     2404851.786      678237.923     2404875.731      678318.134
       2404877.7      678499.475     2404943.585      678600.852
     2404973.951      678821.397     2404949.156      678903.984
     2404955.208      679065.832     2404884.174      679215.065
     2404945.255      679377.269     2404952.909      679535.275
     2404806.719      679642.336     2404794.484      679693.199
     2404806.496       679971.59     2404863.957       680270.61
     2404789.896      680474.304     2404828.496      680738.094

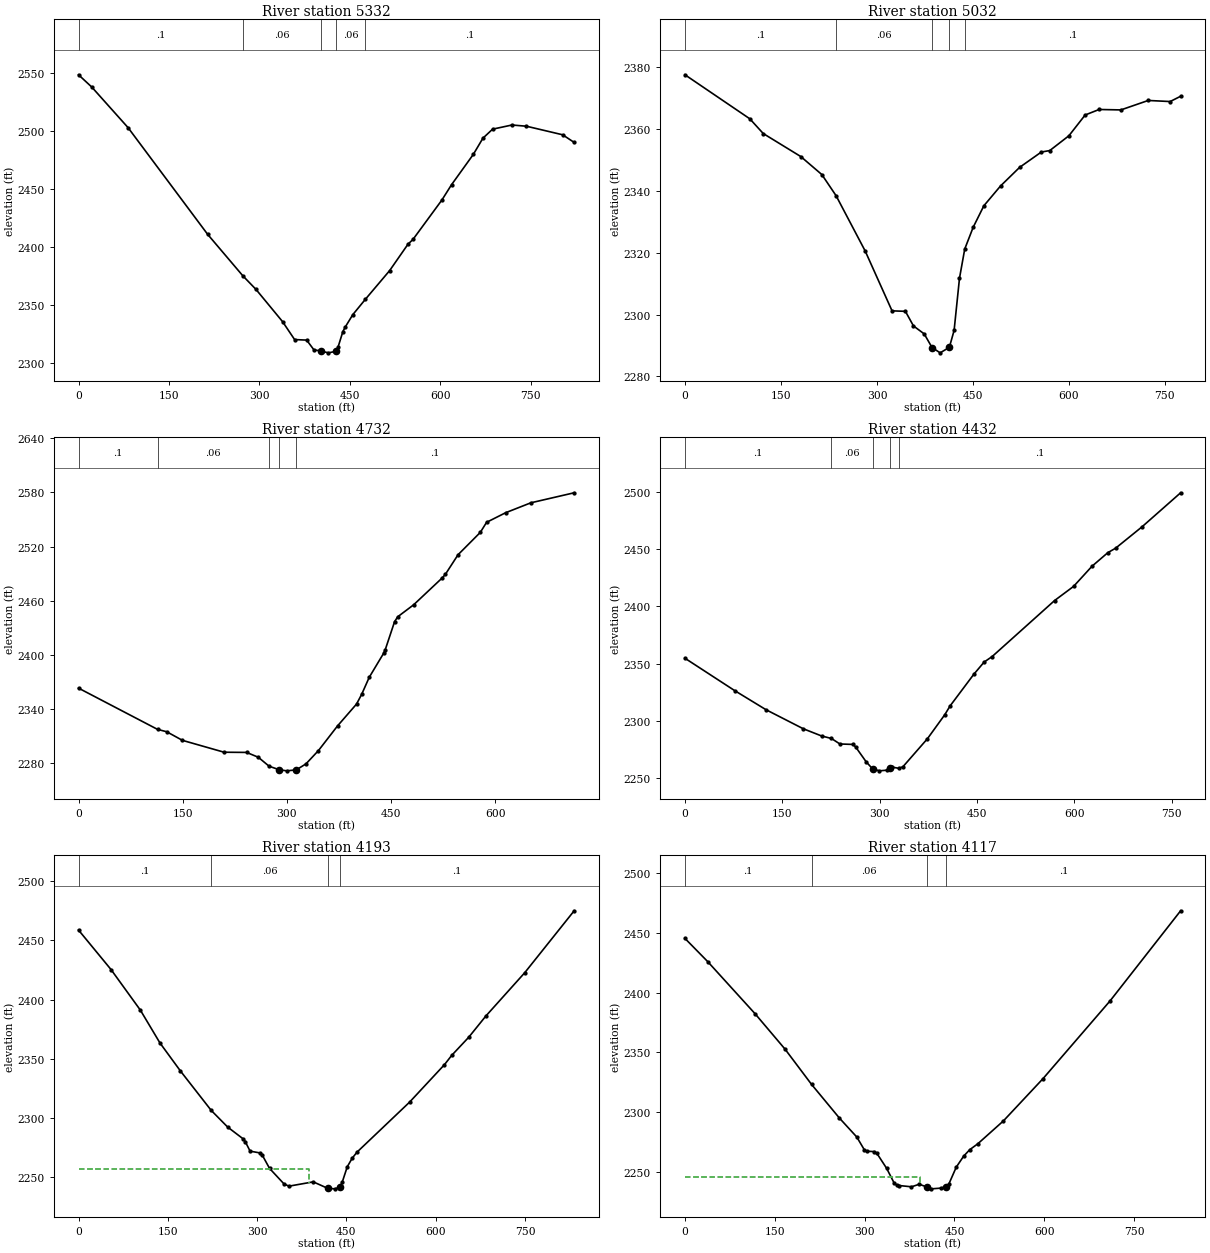
Type RM Length L Ch R = 1 ,5332    ,302.5,300,292.4
XS GIS Cut Line= 3
     2404608.798      675867.519     2405017.623      675888.034
2405429.82450242675909.222033819
#Sta/Elev= 30
       0 2548.77      22 2538.18    82.1 2503.23   214.2 2411.14  272.66 2375.32
   294.3  2363.7   338.4 2335.89   358.4  2320.4   378.4 2319.93   390.4 2311.57
   401.82310.512   414.5 2308.95  427.18 2310.28   430.5 2313.93   438.5 2327.33
   442.5  2331.3     455 2341.92  475.812355.143     516 2379.85   546.6 2402.74
   554.7 2406.73   602.7 2440.74   618.7 2453.95   654.8 2480.08   670.8  2494.1
   686.8 2501.86   718.9 2505.45   742.9 2504.41     803 2497.02   822.1 2490.43
#Mann= 5 ,-1 , 0
       0      .1       0  272.66     .06       0   401.8    .045       0
  427.18     .06       0  475.81      .1       0
Bank Sta=401.8,427.18
XS Rating Curve= 0 ,0
Exp/Cntr=0.3,0.1

Type RM Length L Ch R = 1 ,5032    ,288.6,300,310.5
XS GIS Cut Line= 3
2404710.11892983 676286.48405827     2405090.706      676166.651
2405442.14782191676034.016712352
#Sta/Elev= 30
       0  2377.6   101.3 2363.36   122.3 2358.59     181 2351.14   213.9 2345.31
  236.112338.487   281.6 2320.59   323.6 2301.22   344.5 2301.06   357.1 2296.33
   373.9 2293.75   386.1 2289.35   398.8 2287.63   413.2 2289.42   420.6  2294.9
     429 2311.76   437.22321.221   450.4 2328.26   467.1 2335.22   493.1 2341.61
     523 2347.65   556.9  2352.6   570.1 2353.08     600 2357.87   625.4 2364.59
   647.2 2366.37   681.2 2366.23     724 2369.29   758.2 2368.94   774.6 2370.65
#Mann= 5 ,-1 , 0
       0      .1       0  236.11     .06       0   386.1    .045       0
   413.2     .06       0   437.2      .1       0
Bank Sta=386.1,413.2
XS Rating Curve= 0 ,0
Exp/Cntr=0.3,0.1

Type RM Length L Ch R = 1 ,4732    ,302.7,300,292.8
XS GIS Cut Line= 3
2404775.27404967676278.008009783     2405040.262      676422.033
2405401.08511663676621.249980435
#Sta/Elev= 30
       0 2363.25   113.82317.569   127.1 2314.92   149.6 2305.43   209.7 2292.26
   242.1 2292.06   258.9  2286.7  274.542276.738   289.3 2272.83   299.9 2271.66
   313.6 2272.73   327.6 2279.39   345.6 2294.17     373 2321.38   400.4 2345.62
   407.8 2356.39   418.7 2375.27   439.5 2401.96   441.5 2405.24   455.2 2436.89
   459.8 2442.31   482.6 2455.49   523.8 2485.28   528.3 2489.21   546.6 2510.96
   578.6 2535.66   587.7 2546.85   615.1 2557.45   651.4 2568.43   713.8 2579.54
#Mann= 5 ,-1 , 0
       0      .1       0   113.8     .06       0  274.54      .1       0
   289.3    .045       0   313.6      .1       0
Bank Sta=289.3,313.6
XS Rating Curve= 0 ,0
Exp/Cntr=0.3,0.1

Type RM Length L Ch R = 1 ,4432    ,240.8,238.2,232.7
XS GIS Cut Line= 3
2404581.66871305676631.152608704     2404879.271      676666.085
     2405337.615      676737.933
#Sta/Elev= 30
       0 2354.59    76.4 2326.42   124.7 2309.73   182.3 2293.05   210.5 2286.76
  225.622284.589   238.7 2279.77   258.8 2279.39   262.9  2277.2     279 2264.31
   289.1 2257.97   299.6 2256.33   311.3 2256.92   315.3 2258.41   319.4 2259.53
  329.242258.573   335.6 2259.79   373.4 2284.28   400.3 2305.35   408.4 2312.97
   444.9 2340.57   460.9  2351.3   473.2 2356.08   569.4 2404.97   598.7 2417.34
   627.1 2434.94   651.4 2446.76   663.5  2450.7     704 2469.27   763.6 2499.04
#Mann= 5 ,-1 , 0
       0      .1       0  225.62     .06       0   289.1    .045       0
   315.3     .06       0  329.24      .1       0
Bank Sta=289.1,315.3
XS Rating Curve= 0 ,0
Exp/Cntr=0.3,0.1

Type RM Length L Ch R = 1 ,4193    ,76.8,76.1,74.4
XS GIS Cut Line= 3
2404525.51044148676969.4580580742404730.30167092676922.060961303
2405340.20393503 676798.64965273
#Sta/Elev= 30
       0 2458.77    54.6 2425.36   103.9 2391.03   136.8 2363.26     171  2339.7
   222.9 2306.23   250.6  2292.1     276 2282.37     280  2279.9   288.2 2271.77
   304.5  2270.3   308.3 2268.75   320.8 2257.23   345.3 2243.98   353.5 2242.17
   394.3  2245.8   418.8 2240.28     431  2239.9   439.2 2241.52   443.3  2246.1
   451.4 2258.56   459.6 2265.75   467.8 2270.95   556.1 2313.24   614.7 2344.95
   626.9 2352.81   655.5 2368.15   684.1    2386   749.4 2422.63   832.5 2475.05
#Mann= 4 ,-1 , 0
       0      .1       0   222.9     .06       0   418.8    .045       0
   439.2      .1       0
#XS Ineff= 2 , 0
          387.05 2257.06
Permanent Ineff=
       F       F
Bank Sta=418.8,439.2
XS Rating Curve= 0 ,0
Exp/Cntr(USF)=0,0
Exp/Cntr=0.3,0.1

Type RM Length L Ch R = 1 ,4117    ,370.1,379,374.4
XS GIS Cut Line= 3
2404558.36033659677064.2527919082404956.68433659676953.350791908
2405356.33833659676845.015791908
#Sta/Elev= 30
       0 2445.52    37.8 2426.17   116.7 2382.58   167.1 2352.69  211.28 2323.18
   257.8 2294.95   286.9 2279.01   299.4 2268.37   303.5  2267.1     316 2266.82
   320.1 2265.58   336.7 2252.78   349.2  2240.5   353.3 2238.83   357.5 2238.36
   378.2 2237.29   391.2 2239.43   404.2 2237.07   411.5 2235.58   426.9 2236.16
   436.3 2237.52   440.5 2239.51     453  2253.8   465.3 2262.97   475.4 2268.38
   488.9 2273.34   531.7 2292.54     598 2328.07   709.9 2393.23   827.6 2468.71
#Mann= 4 ,-1 , 0
       0      .1       0  211.28     .06       0   404.2    .045       0
   436.3      .1       0
#XS Ineff= 2 , 0
          392.08 2245.24
Permanent Ineff=
       F       F
Bank Sta=404.2,436.3
XS Rating Curve= 0 ,0
Exp/Cntr=0.3,0.1

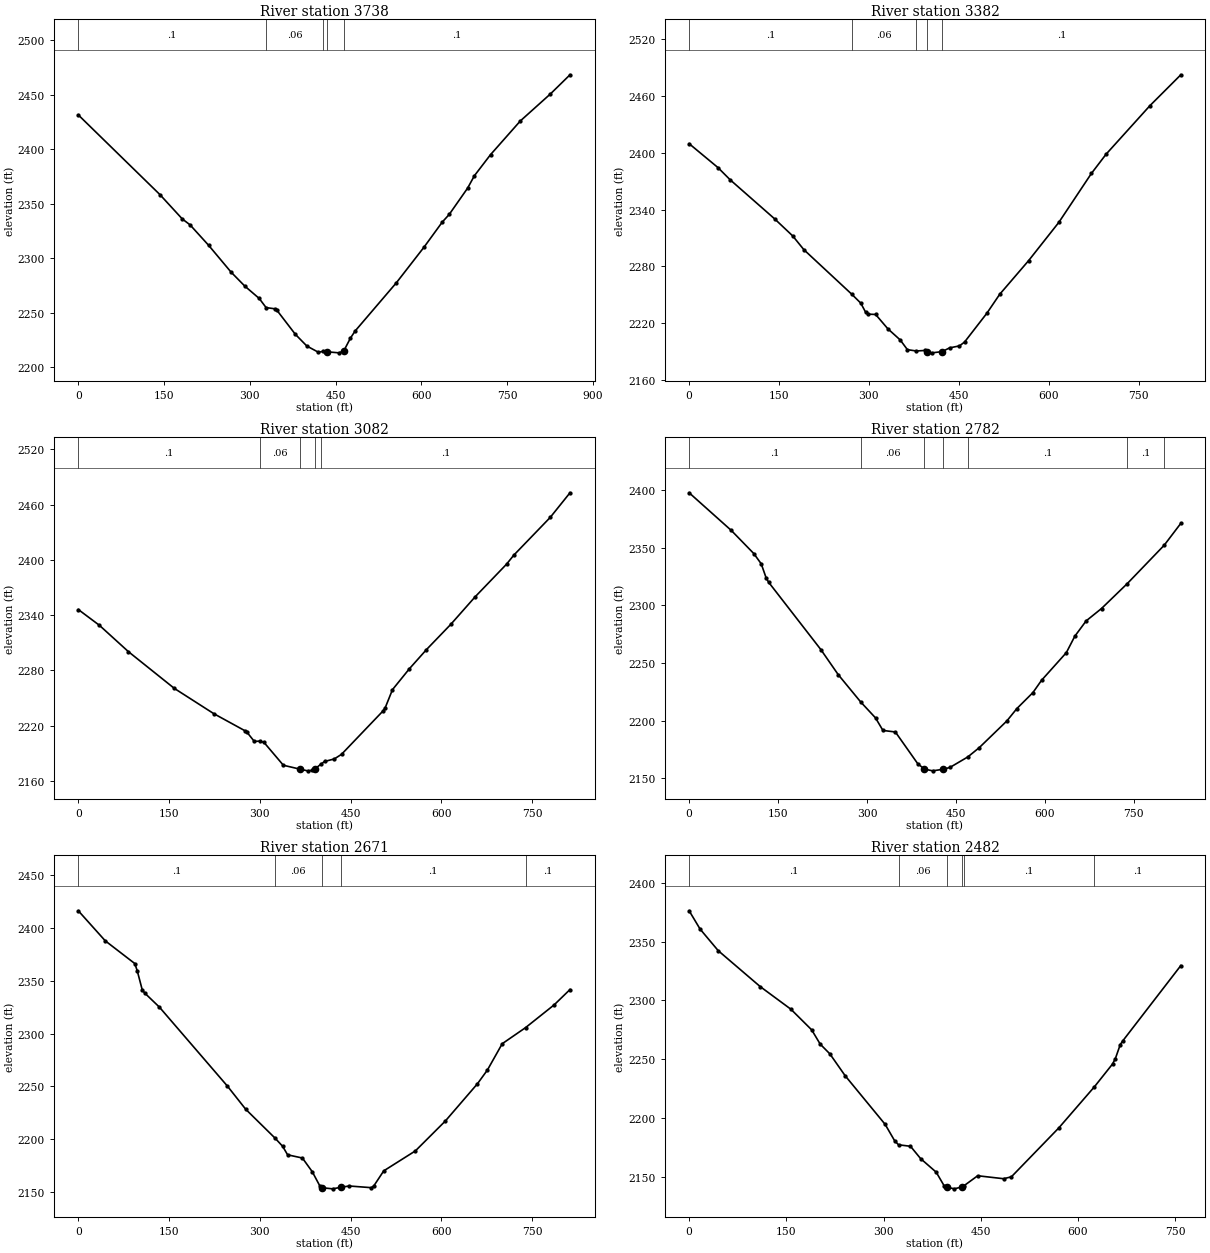
Type RM Length L Ch R = 1 ,3738    ,349.3,356.7,359.1
XS GIS Cut Line= 2
2404680.67227739677311.5777431262405537.19938914677236.217149505
#Sta/Elev= 30
       0 2431.47   142.8 2358.35     182 2335.97   195.3 2330.71   227.7 2312.01
   267.1 2287.32   291.2 2274.45   316.3 2263.18  328.352254.782   343.4 2253.69
   347.4 2252.24   379.5 2230.28   399.6 2219.54   419.7 2213.85  427.932214.603
   435.7 2214.19   455.8 2213.28   464.22215.025   475.9 2226.82   483.9 2233.21
   556.2 2277.57   604.4 2310.12   636.5 2333.25   648.6 2340.23   680.7  2364.3
   692.7 2375.78   720.8 2395.02     773 2425.99   825.6 2450.75   859.8  2468.3
#Mann= 5 ,-1 , 0
       0      .1       0  328.35     .06       0  427.93      .1       0
   435.7    .045       0   464.2      .1       0
Bank Sta=435.7,464.2
XS Rating Curve= 0 ,0
Exp/Cntr=0.3,0.1

Type RM Length L Ch R = 1 ,3382    ,300.8,300,296.5
XS GIS Cut Line= 3
     2404692.068      677522.978     2405090.852      677617.591
     2405487.097      677725.909
#Sta/Elev= 30
       0  2409.6      48 2384.39    68.5  2371.4   142.5 2330.21   172.9 2312.03
   191.5 2297.49  271.512250.343   286.4    2241   294.6 2231.31   298.7 2229.31
   311.2 2229.01   331.6 2213.87   352.2 2202.09   364.3 2191.77  379.052190.386
   393.3  2190.9   397.4 2189.19   405.6 2188.41   422.2 2189.71   434.6 2193.65
   451.2 2195.76   459.7 2199.86   496.8 2230.21   518.3 2250.31   566.5 2285.88
   617.1 2326.48   671.3 2378.08   695.9 2398.51     769  2449.8   820.6 2482.48
#Mann= 5 ,-1 , 0
       0      .1       0  271.51     .06       0  379.05      .1       0
   397.4    .045       0   422.2      .1       0
Bank Sta=397.4,422.2
XS Rating Curve= 0 ,0
Exp/Cntr=0.3,0.1

Type RM Length L Ch R = 1 ,3082    ,295.5,300,300.5
XS GIS Cut Line= 3
2404603.96053426 677874.32644522     2404982.015      677883.982
2405415.38413829677913.982911956
#Sta/Elev= 30
       0 2346.09    34.8    2329    82.8 2300.36   158.8 2260.42     224    2233
   274.9 2214.67   278.9 2212.72   290.9 2202.89  299.81 2203.24   306.9  2201.8
   338.9 2177.01   366.1 2172.83   378.9 2170.96   386.9 2171.42   390.9 2172.99
  401.092178.285     407 2181.14     423 2183.86     435 2188.89   503.2 2235.72
   507.2 2239.45   519.2 2259.11   547.3 2281.91   575.4 2302.61   615.5 2329.95
   655.8 2359.89   707.7 2395.32   719.7 2405.12   779.9 2446.11   812.6 2472.86
#Mann= 5 ,-1 , 0
       0      .1       0  299.81     .06       0   366.1    .045       0
   390.9     .06       0  401.09      .1       0
Bank Sta=366.1,390.9
XS Rating Curve= 0 ,0
Exp/Cntr=0.3,0.1

Type RM Length L Ch R = 1 ,2782    ,115.6,110.6,100.7
XS GIS Cut Line= 3
 2404502.6908715678037.740266788     2404895.973      678160.673
     2405295.743      678280.519
#Sta/Elev= 30
       0 2397.88    71.2 2365.12     109 2345.11   121.6 2336.17     130 2323.75
   134.2 2320.08   222.2 2261.63   251.5 2239.85  289.412216.119   314.4 2202.28
   326.9 2191.39   347.9 2190.05   385.6  2162.5   396.9 2157.79   410.8 2156.29
   428.9 2157.68     440 2159.27  470.082168.375   489.4 2176.45     536 2199.67
   552.7 2210.33   579.9 2224.28   594.5 2234.98   636.3    2259   650.6 2273.28
   669.7 2286.58   695.6 2297.33  739.172319.025   801.32352.281   829.4 2371.33
#Mann= 7 ,-1 , 0
       0      .1       0  289.41     .06       0   396.9    .045       0
   428.9     .06       0  470.08      .1       0  739.17      .1       0
   801.3      .1       0
Bank Sta=396.9,428.9
XS Rating Curve= 0 ,0
Exp/Cntr=0.3,0.1

Type RM Length L Ch R = 1 ,2671    ,186.1,189.4,191.1
XS GIS Cut Line= 3
2404447.06437104678334.8408433642405010.31353675678227.163138926
2405244.54128007678275.054182711
#Sta/Elev= 30
       0 2416.02    44.5 2387.63    93.3 2366.14    97.4 2359.26   105.6 2341.35
   109.6 2338.32   134.1 2324.87   246.4 2250.27   276.6  2228.4   324.72201.324
   337.7 2193.34   345.8 2185.34   370.3 2182.29   386.6 2169.33   398.8 2156.24
   402.5 2154.24   420.2 2153.16   433.9 2154.63   447.6 2155.85   484.3 2154.26
   488.4 2156.03   504.7 2170.15     557 2189.03   606.6 2217.34   659.6 2252.52
     676 2265.47   700.5 2290.35  739.032305.543   786.2 2327.02   812.5 2341.58
#Mann= 5 ,-1 , 0
       0      .1       0   324.7     .06       0   402.5    .045       0
   433.9      .1       0  739.03      .1       0
Bank Sta=402.5,433.9
XS Rating Curve= 0 ,0
Exp/Cntr(USF)=0,0
Exp/Cntr=0.3,0.1

Type RM Length L Ch R = 1 ,2482    ,176,170.9,165.1
XS GIS Cut Line= 3
     2404469.837      678425.893     2404877.958       678441.78
2405228.06471365678438.193741667
#Sta/Elev= 30
       0 2376.43    16.9 2360.84    44.9 2342.43   109.7 2311.82     157 2292.56
   189.1 2274.96   202.2 2262.84   217.1 2254.54   240.7 2235.91   302.4 2194.48
   317.1 2180.47  323.082177.071   341.5 2175.81   357.2 2165.26   381.2 2153.73
   393.2 2142.35   397.2    2141   409.2 2139.55   421.2 2141.26  424.27 2142.28
   445.2  2150.7   485.2 2148.17   497.2  2149.8   570.5 2191.55  625.172226.429
   653.2 2245.88   657.6 2250.52   665.2  2262.5   669.2 2265.73   758.6 2329.76
#Mann= 6 ,-1 , 0
       0      .1       0  323.08     .06       0   397.2    .045       0
   421.2     .06       0  424.27      .1       0  625.17      .1       0
Bank Sta=397.2,421.2
XS Rating Curve= 0 ,0
Exp/Cntr=0.3,0.1

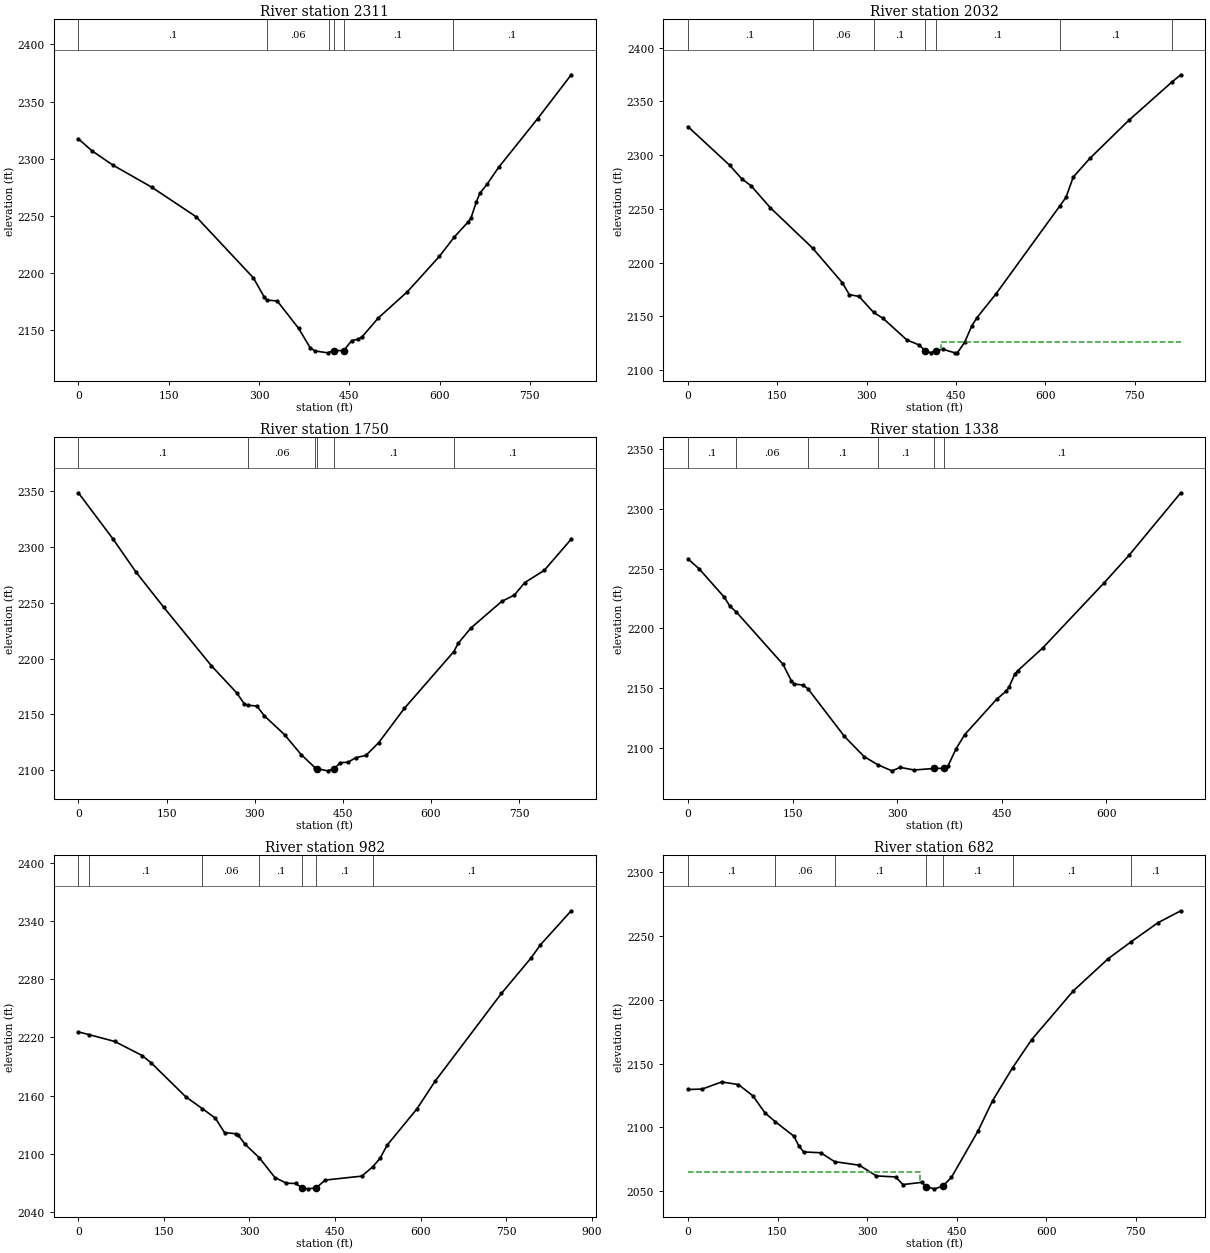
Type RM Length L Ch R = 1 ,2311    ,273.2,279.1,281.8
XS GIS Cut Line= 3
2404542.09820176 678761.65952674 2404813.7052418678649.180069166
2405289.47780847678428.009208438
#Sta/Elev= 30
       0 2317.34    22.3 2306.95    57.7 2294.23     122 2274.94   195.5 2249.15
   290.8 2195.55   308.5 2178.95   312.8 2176.23   330.4 2175.31   365.7 2151.45
   384.8 2134.59   392.8 2131.64   413.9 2129.94   424.22131.987   440.7 2131.85
   453.9 2140.59   465.1 2141.93   471.6 2144.17     498 2160.38   546.6  2183.5
   599.5 2214.32   624.7 2231.55     648 2244.88   652.4 2248.35   661.2 2262.39
   666.9 2269.66     679 2277.71   697.9 2292.25   762.7 2334.91   818.6 2373.43
#Mann= 6 ,-1 , 0
       0      .1       0  313.89     .06       0  415.97      .1       0
   424.2    .045       0   440.7      .1       0   621.5      .1       0
Bank Sta=424.2,440.7
XS Rating Curve= 0 ,0
Exp/Cntr=0.3,0.1

Type RM Length L Ch R = 1 ,2032    ,276.6,281.9,285.5
XS GIS Cut Line= 3
      2404549.02      678820.468     2404955.525      678858.787
     2405368.954       678925.64
#Sta/Elev= 30
       0 2326.47      70 2290.52    90.1 2278.06   106.2  2271.3   138.3 2250.97
  209.082213.517   258.9 2181.34   270.9 2170.09     287 2168.52  311.712153.525
   327.2 2148.19   367.3 2128.04   387.4 2123.44  398.59 2117.86   407.5 2116.15
   415.82117.878   427.8 2119.29     448 2115.98   452.1 2115.99   464.2 2125.61
   476.4 2141.03   484.5 2148.36   516.9 2170.76  623.792252.408   634.5 2260.68
   646.6 2279.55   674.9 2297.13   739.8 2332.26  811.542367.621   827.1  2374.7
#Mann= 7 ,-1 , 0
       0      .1       0  209.08     .06       0  311.71      .1       0
  398.59    .045       0   415.8      .1       0  623.79      .1       0
  811.54      .1       0
#XS Ineff= 2 , 0
                             425         2125.72
Permanent Ineff=
       F       F
Bank Sta=398.59,415.8
XS Rating Curve= 0 ,0
Exp/Cntr=0.3,0.1

Type RM Length L Ch R = 1 ,1750    ,417.7,411.9,403.6
XS GIS Cut Line= 3
2404527.67121787678976.4950893722404906.36121787679123.212089372
2405303.40218853679294.298305918
#Sta/Elev= 30
       0 2348.82    59.1 2307.26    97.7  2277.9   144.9 2246.33   226.4  2193.6
   269.3 2169.38   282.1 2159.64  287.942158.219   303.6 2157.53   316.4 2148.73
   350.8  2131.8   379.3  2113.8  403.072101.965   406.2 2101.36     424 2099.36
   435.6  2101.4   445.7 2106.72   458.8 2107.06   471.9 2111.16   489.3 2113.22
   511.1 2124.72   554.6 2155.39  638.57 2206.19   646.6 2214.01   667.9 2227.52
   720.1 2251.29   741.9 2257.09   759.3 2268.16   792.7 2279.25   838.5  2307.2
#Mann= 6 ,-1 , 0
       0      .1       0  287.94     .06       0  403.07      .1       0
   406.2    .045       0   435.6      .1       0  638.57      .1       0
Bank Sta=406.2,435.6
XS Rating Curve= 0 ,0
Exp/Cntr=0.3,0.1

Type RM Length L Ch R = 1 ,1338    ,360.8,356.2,352.5
XS GIS Cut Line= 2
2404594.47032548679499.7653646142405300.53528768679533.434294808
#Sta/Elev= 30
       0 2258.07    16.3 2249.66    52.3 2225.99    60.3 2218.45   69.052213.963
   136.4 2170.01   148.4 2156.08   152.4 2153.52   164.5 2152.79  172.112149.654
   224.5 2109.82   252.6 2093.03  272.082086.228   292.6 2081.07   304.6 2083.95
   324.3 2081.77   352.32083.025   366.82083.156   372.7 2084.84   384.7 2099.57
   396.9 2111.24   442.7  2140.8   456.8 2147.82   460.8 2151.39   468.8  2161.8
   472.8 2164.54   508.9 2183.72     597  2238.1     633 2261.29   706.9 2313.29
#Mann= 6 ,-1 , 0
       0      .1       0   69.05     .06       0  172.11      .1       0
  272.08      .1       0   352.3    .045       0   366.8      .1       0
Bank Sta=352.3,366.8
XS Rating Curve= 0 ,0
Exp/Cntr=0.3,0.1

Type RM Length L Ch R = 1 ,982     ,299.8,300,296.8
XS GIS Cut Line= 3
2404395.30032681679824.484069807     2404800.911      679791.776
2405256.67121856679756.834538954
#Sta/Elev= 30
       0  2225.6   18.242222.881    63.7 2215.76   111.8 2201.25   127.9 2193.54
   188.1 2158.77  217.512146.373   240.2 2136.59   256.3  2121.7   276.3 2120.55
   280.4 2118.92   292.4 2109.67  317.152095.816   344.6 2075.36   364.6 2069.54
   380.7 2069.22   392.7 2064.68     402 2063.71   416.9  2064.7   432.8 2072.77
     497 2076.83  516.46 2086.69   529.1 2095.37   541.2 2108.72   593.3 2146.01
   625.4 2174.75   741.7 2265.32   793.9 2302.09   809.9 2315.36     864 2350.57
#Mann= 7 ,-1 , 0
       0      .1       0   18.24      .1       0  217.51     .06       0
  317.15      .1       0   392.7    .045       0   416.9      .1       0
  516.46      .1       0
Bank Sta=392.7,416.9
XS Rating Curve= 0 ,0
Exp/Cntr=0.3,0.1

Type RM Length L Ch R = 1 ,682     ,198.2,199.7,201.9
XS GIS Cut Line= 3
     2404419.249      680152.098     2404822.881      680087.596
2405232.31750489680010.538407826
#Sta/Elev= 30
       0 2129.66    23.8 2129.99    56.5 2135.57    84.6 2133.52   108.9 2124.62
   129.1 2111.32  146.292104.416   177.7 2092.99   185.8 2085.38   193.9 2080.74
   222.3 2080.12   245.62073.153   287.1 2070.35   315.4 2061.98   347.9 2061.15
     360 2055.18   392.4 2056.98   398.1 2053.59   412.6 2051.85   426.4 2053.78
   441.2 2060.76   485.9 2097.22   510.4 2121.03   543.62146.596   575.5 2168.63
   645.6 2206.99   703.8 2232.09   742.32245.375   787.1 2260.25   825.4 2269.63
#Mann= 7 ,-1 , 0
       0      .1       0  146.29     .06       0   245.6      .1       0
   398.1    .045       0   426.4      .1       0   543.6      .1       0
   742.3      .1       0
#XS Ineff= 2 , 0
          388.83 2064.74
Permanent Ineff=
       F       F
Bank Sta=398.1,426.4
XS Rating Curve= 0 ,0
Exp/Cntr=0.3,0.1

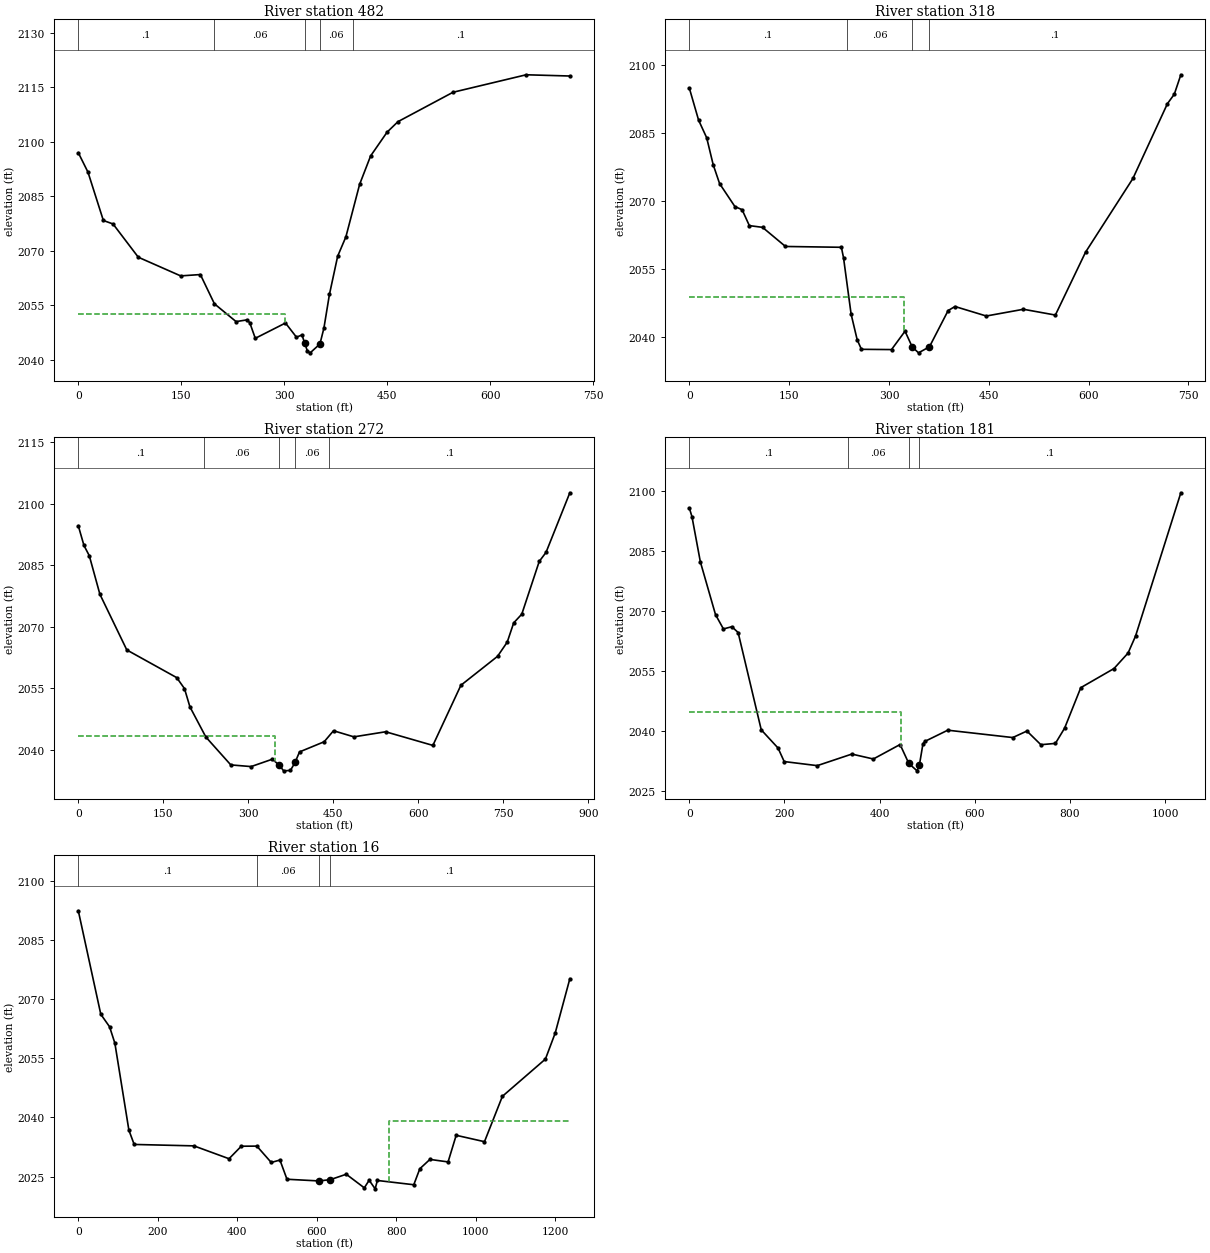
Type RM Length L Ch R = 1 ,482     ,161.1,163.5,163.7
XS GIS Cut Line= 3
2404573.70504447680168.4371495392404674.06836305680278.721017038
2405240.90994027680286.320573074
#Sta/Elev= 30
       0 2096.96    14.1 2091.62    36.5 2078.34    50.6 2077.38    87.4 2068.24
   149.1 2063.11   177.8 2063.48   198.3 2055.43   229.8 2050.55   245.8 2051.02
   249.8 2050.23   257.8 2045.95   301.8 2050.16   317.8 2046.26   325.8 2046.88
   329.8 2044.62   333.8 2042.41   337.8 2041.96     3522044.408   357.8 2048.79
   365.8    2058   377.8 2068.52   389.8 2073.85   409.8 2088.28   425.8 2096.08
   449.8 2102.62   465.7 2105.51   545.8 2113.58   652.4 2118.39     716 2118.05
#Mann= 5 ,-1 , 0
       0      .1       0  197.84     .06       0   329.8    .045       0
     352     .06       0  399.56      .1       0
#XS Ineff= 2 , 0
          300.73 2052.74
Permanent Ineff=
       F       F
Bank Sta=329.8,352
XS Rating Curve= 0 ,0
Exp/Cntr(USF)=0,0
Exp/Cntr=0.3,0.1

Type RM Length L Ch R = 1 ,318     ,51.5,46.3,44.8
XS GIS Cut Line= 4
2404568.27516853680209.7655666112404716.09614237680414.154879464
2404938.72121743680455.5671797072405161.49551238680321.848264726
#Sta/Elev= 30
       0 2094.96      14 2087.84    26.1 2083.97    35.9    2078    45.5 2073.84
    68.5 2068.76    79.3 2068.07    90.2 2064.55     110 2064.17   144.5 2059.94
   228.5 2059.76   231.7 2057.45   243.1 2044.98   252.2 2039.33   258.6 2037.21
   303.8 2037.15   324.1 2041.21   334.92037.743   344.4 2036.43   360.82037.767
   388.9 2045.78   399.2 2046.67   446.2 2044.57     502 2046.06     550 2044.78
   595.3 2058.67   666.5 2074.97   718.3 2091.49   728.7  2093.6   738.5 2097.89
#Mann= 4 ,-1 , 0
       0      .1       0     237     .06       0   334.9    .045       0
   360.8      .1       0
#XS Ineff= 2 , 0
          323.22 2048.83
Permanent Ineff=
       F       F
Bank Sta=334.9,360.8
XS Rating Curve= 0 ,0
Exp/Cntr(USF)=0,0
Exp/Cntr=0.3,0.1

Type RM Length L Ch R = 1 ,272     ,90.2,90.7,90.2
XS GIS Cut Line= 4
 2404565.7528237680214.295156147 2404721.7364805680472.150608436
2404999.62966142680476.9559862032405238.26862671680315.306535187
#Sta/Elev= 30
       0 2094.66      10 2089.85    19.4 2087.35    38.1 2077.94    85.6 2064.34
   173.7 2057.58   187.4  2054.9     197 2050.44   225.1 2043.08   269.1 2036.27
     305 2035.86   342.4 2037.66   354.62036.207   362.4 2034.82   374.4 2034.92
   382.62036.883   390.4 2039.44   433.9 2041.92   450.4 2044.61   486.4 2043.12
   542.4 2044.36   625.8 2041.03   675.2 2055.71   739.9 2062.78     757 2066.25
   768.4 2070.95   782.7 2073.08   813.5 2085.96   825.5 2088.17   867.5 2102.72
#Mann= 5 ,-1 , 0
       0      .1       0   221.4     .06       0   354.6    .045       0
   382.6     .06       0  442.41      .1       0
#XS Ineff= 2 , 0
          347.35 2043.21
Permanent Ineff=
       F       F
Bank Sta=354.6,382.6
XS Rating Curve= 0 ,0
Exp/Cntr(USF)=0,0
Exp/Cntr=0.3,0.1

Type RM Length L Ch R = 1 ,181     ,165.7,165.7,165.7
XS GIS Cut Line= 4
2404538.55694165680229.8557286612404689.47152162 680553.93242057
2404987.09528034680575.0967767462405264.87745515680319.801730373
#Sta/Elev= 30
       0 2095.68     5.6 2093.49    23.2 2082.21    55.1    2069    71.7 2065.43
    89.4 2065.99   102.6 2064.54   151.2 2040.21   186.5 2035.66   199.4 2032.28
   268.9 2031.26   341.6 2034.15   386.8 2032.92     443 2036.54   461.4  2031.8
   478.7 2029.96   483.72031.488   491.1 2036.73   495.1 2037.32   543.2 2040.12
   679.8 2038.28   709.6 2039.91   738.9 2036.49   769.5 2036.82   788.8 2040.63
   822.8 2050.75   892.6 2055.53   922.2 2059.41   937.9 2063.65  1033.1 2099.47
#Mann= 4 ,-1 , 0
       0      .1       0  332.66     .06       0   461.4    .045       0
   483.7      .1       0
#XS Ineff= 2 , 0
          445.34 2044.79
Permanent Ineff=
       F       F
Bank Sta=461.4,483.7
XS Rating Curve= 0 ,0
Exp/Cntr(USF)=0,0
Exp/Cntr=0.3,0.1

Type RM Length L Ch R = 1 ,16      ,,,
XS GIS Cut Line= 4
2404500.19469999 680231.660534472404723.73291056680707.226226228
2404941.54332461680747.3593539722405244.05796039680361.906106967
#Sta/Elev= 30
       0 2092.38    56.6 2066.15    78.7 2062.98      92 2058.83   127.3 2036.77
   140.6 2033.16   290.9  2032.8   379.3 2029.54   410.1 2032.71   449.3 2032.74
   485.5 2028.59   507.4 2029.21   525.1 2024.34   605.8 2023.91   634.3 2024.24
   674.3 2025.61   719.7 2022.16   731.9 2024.09     747 2021.91   752.6 2024.03
   844.2 2022.95   859.4    2027   884.8 2029.37   930.5 2028.73   950.9 2035.48
  1022.1 2033.86  1067.2 2045.36  1175.5  2054.8  1200.1  2061.4  1236.9 2075.15
#Mann= 4 ,-1 , 0
       0      .1       0  449.81     .06       0   605.8    .045       0
   634.3      .1       0
#XS Ineff= 2 , 0
                          781.93            2039
Permanent Ineff=
       F       F
Bank Sta=605.8,634.3
XS Rating Curve= 0 ,0
Exp/Cntr(USF)=0,0
Exp/Cntr=0.3,0.1
LCMann Table=0

Chan Stop Cuts=-1
Use User Specified Reach Order=0
Composite Channel Slope=5